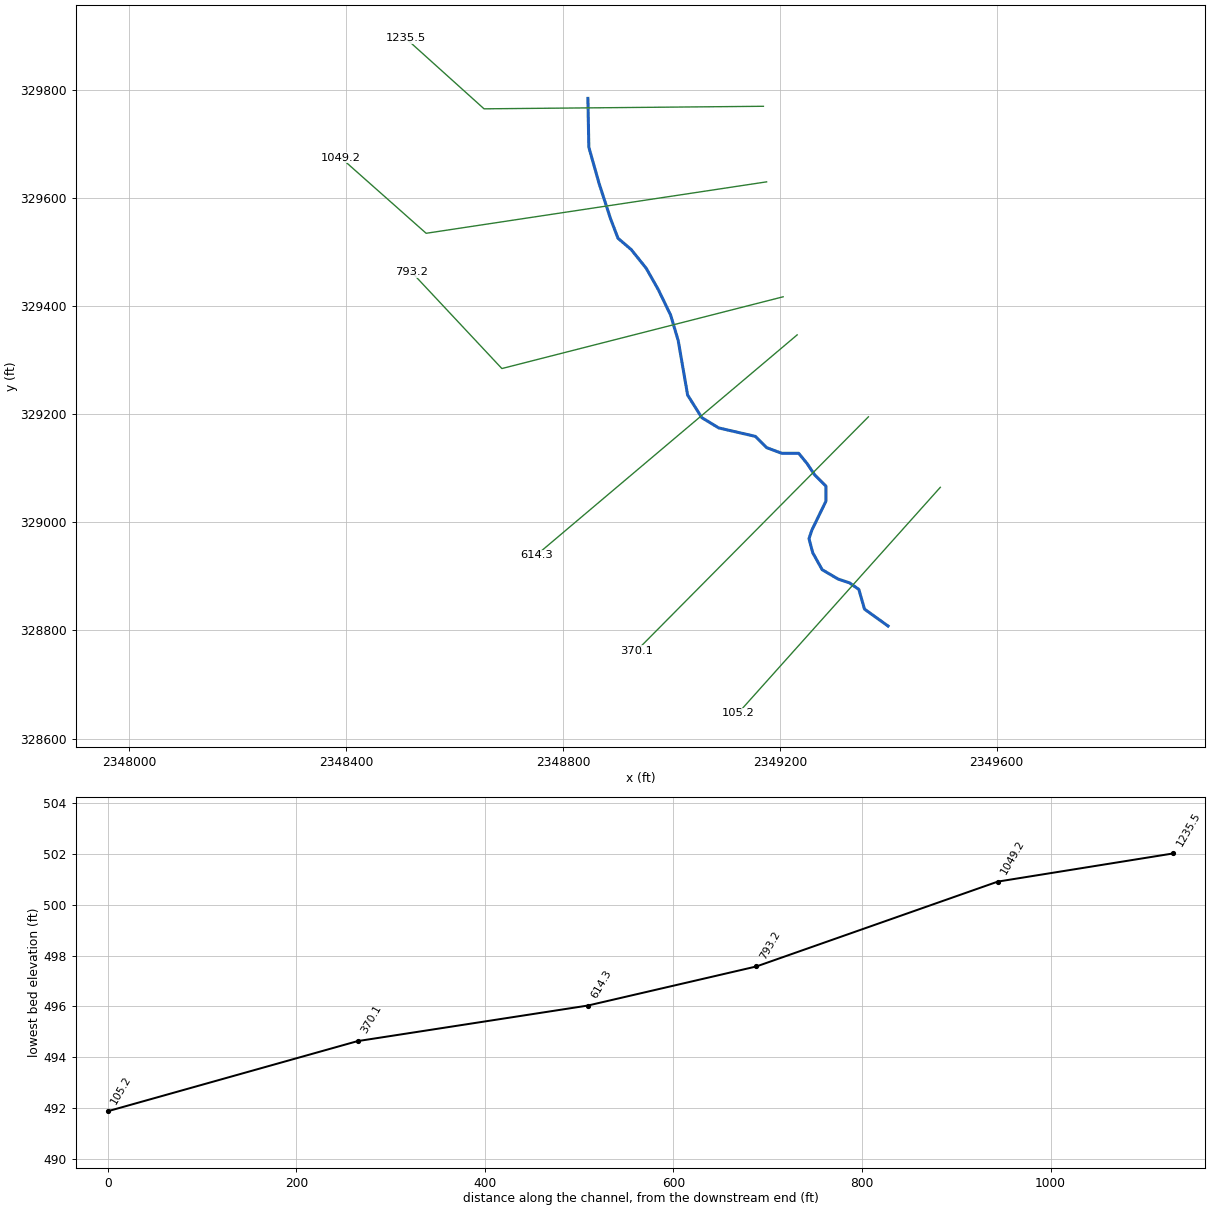
--- BACKTRIB2.prj (project) ---

Proj Title=BACKTRIB2
Current Plan=p01
Default Exp/Contr=0,0
English Units
Geom File=g01
Flow File=f01
Plan File=p01
BEGIN DESCRIPTION:
END DESCRIPTION:
DSS Export Rating Curves= 0
DSS Export Rating Curve Sorted= 0
DSS Export Volume Flow Curves= 0
DXF OffsetX= 0
DXF OffsetY= 0
DXF ScaleX= 0
DXF ScaleY= 0

--- BACKTRIB2.p01 (plan) ---

Plan Title=Floodplain
Program Version=4.00
Geom File=g01
Flow File=f01
K Sum by GR=0
Std Step Tol=0.01
Critical Tol=0.01
Num of Std Step Trials=20
Max Error Tol=0.3
Flow Tol Ratio=0.001
Split Flow NTrial=30
Split Flow Tol=0.02
Split Flow Ratio=0.02
Log Output Level=0
Friction Slope Method=1
Unsteady Friction Slope Method=2
Unsteady Bridges Friction Slope Method=1
Global Log Level=0
CheckData=False
Run HTab=0
Run UNet=0
Run PostProcess=0
UNET Theta=0
UNET Theta Warmup=0
UNET ZTol=0
UNET ZSATol=0
UNET MxIter=0
UNET MaxInSteps=0
UNET DtIC=0
UNET DtMin=0
UNET MaxCRTS=0
UNET WFStab=0
UNET SFStab=0
UNET WFX=0
UNET SFX=0
UNET DSS MLevel=0
UNET DZMax Abort=0
UNET Convert EG Bridges=0
UNET Use Existing IB Tables=0
UNET Froude Limit=0
UNET Froude Power=0
Write IC File=0
Echo Input=False
Echo Output=False
Write Detailed=0

--- BACKTRIB2.f01 (steady flow) ---

Flow Title=NFF Regression Equation
Program Version=4.10
Number of Profiles= 1
Profile Names=P100yr
River Rch & RM=BACKTRIB2,Main            ,1235.5
542.2621
River Rch & RM=BACKTRIB2,Main            ,370.1
571.6247
River Rch & RM=BACKTRIB2,Main            ,105.2
573.4036
Boundary for River Rch & Prof#=BACKTRIB2,Main            , 1
Up Type= 0
Dn Type= 3
Dn Slope=0.01036
DSS Import GetInterval= 0
DSS Import GetPeak= 0
DSS Import FillOption= 0

--- BACKTRIB2.g01 (geometry) ---

Geom Title=USGS 10m DEM
Program Version=4.10

River Reach=BACKTRIB2       ,Main
Reach XY= 30
     2348845.945      329783.901     2348847.681      329693.623
     2348866.778      329625.915     2348887.611      329561.678
       2348901.5       329525.22     2348925.806      329504.387
     2348953.583      329469.665     2348976.153      329429.734
     2348998.722      329382.859     2349012.611      329335.984
     2349029.972       329235.29     2349056.014      329193.623
     2349087.264      329174.526     2349154.972      329158.901
     2349175.806      329138.067     2349203.584      329127.651
     2349234.834      329127.651     2349250.459      329108.553
     2349264.348       329087.72     2349285.181      329066.887
     2349285.181      329039.109     2349259.139       328985.29
     2349253.931      328969.665     2349260.875      328943.623
     2349278.236      328912.373      2349307.75      328895.012
     2349328.584      328888.067     2349345.945      328875.914
     2349356.362      328839.456     2349399.798      328808.186

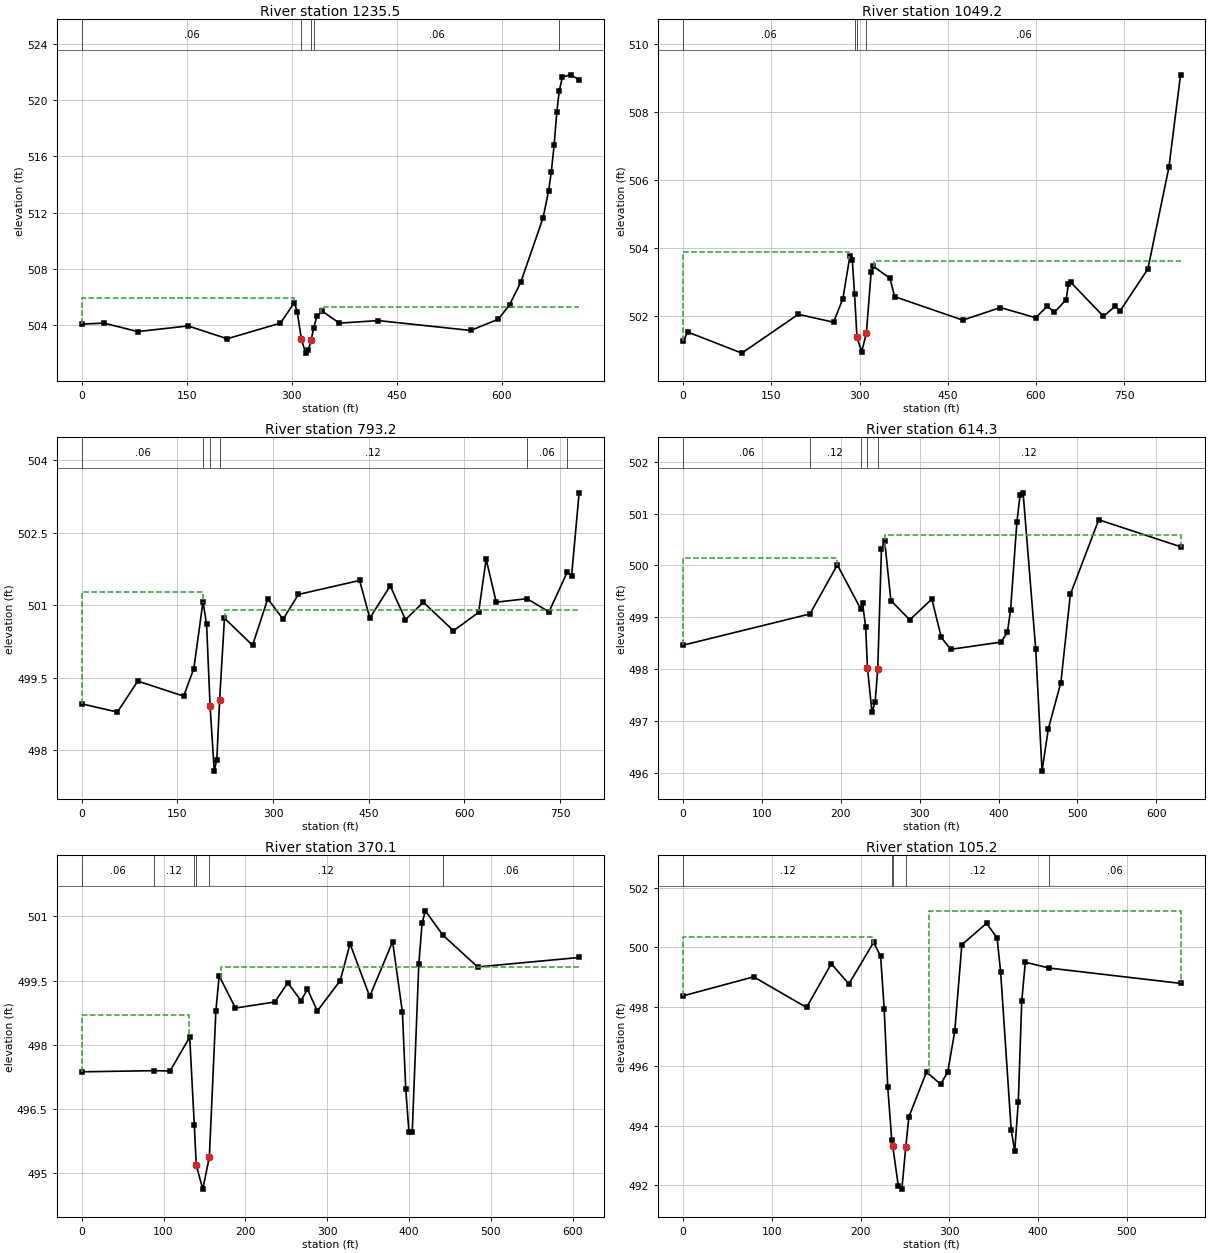
Type RM Length L Ch R = 1 ,1235.5  ,183.2,186.3,189.5
XS GIS Cut Line= 3
     2349169.842      329769.276     2348654.336      329764.579
       2348509.9      329894.923
#Sta/Elev= 30
       0  504.08      32  504.15    79.9  503.55   151.9  503.95   207.8  503.04
   283.7  504.15   303.7  505.61   307.7  504.95  313.66     503   319.7  502.02
   323.7  502.26   327.7  502.98   331.1   503.8   335.7  504.63   343.7  504.99
   367.7  504.15   423.6  504.33   555.2  503.63   594.9  504.43   610.8  505.46
   626.7  507.04   658.5  511.61   666.4   513.5   670.4   514.9   674.4   516.8
   678.3  519.16   681.7520.6475   686.3  521.63   698.2  521.78   710.1  521.43
#Mann= 5 ,-1 , 0
       0     .06       0  313.66    .045       0   327.7    .045       0
   331.1     .06       0   681.7    .016       0
#XS Ineff= 2 , 0
          302.99  505.95  340.97          505.32
Permanent Ineff=
       F       F
Bank Sta=313.66,327.7
XS Rating Curve= 0 ,0
Exp/Cntr=0.3,0.1

Type RM Length L Ch R = 1 ,1049.2  ,253.4,256,258.4
XS GIS Cut Line= 3
     2349175.714      329629.537     2348547.477      329534.421
     2348390.124       329674.16
#Sta/Elev= 30
       0  501.26       8  501.53    99.9  500.91   195.8  502.05   255.8  501.82
   271.7  502.51   283.7  503.77   287.7  503.66   291.5  502.66   295.7  501.37
   303.7  500.95   311.7   501.5   319.7  503.28   323.7  503.46   351.7  503.11
   359.7  502.57   475.6  501.88   539.5  502.25   599.4  501.95   619.4  502.29
   631.4  502.11   651.3  502.48   655.2  502.95   659.2  502.99   714.8  501.99
   734.7  502.29   742.6  502.14   790.2  503.38     826  506.37   845.8  509.09
#Mann= 4 ,-1 , 0
       0     .06       0   291.5    .045       0   295.7    .045       0
   311.7     .06       0
#XS Ineff= 2 , 0
          282.77  503.89  325.08          503.63
Permanent Ineff=
       F       F
Bank Sta=295.7,311.7
XS Rating Curve= 0 ,0
Exp/Cntr=0.3,0.1

Type RM Length L Ch R = 1 ,793.2   ,168.5,178.9,189.2
XS GIS Cut Line= 3
     2349206.245      329416.994     2348687.216      329284.301
     2348520.469       329462.79
#Sta/Elev= 30
       0  498.96      56  498.79      88  499.43   159.9  499.12   175.9  499.69
  190.25501.0721   195.9   500.6   201.3  498.92   207.9  497.57   211.9  497.81
   216.3  499.04   223.9  500.73   267.9  500.17   291.8  501.13   315.8  500.71
   339.8  501.22   435.8  501.51   451.8  500.73   483.8   501.4   507.7   500.7
   535.7  501.06     583  500.47   622.4  500.85   634.2  501.95     650  501.06
  698.25501.1333   732.7  500.86  761.27501.6778   768.2  501.61     780  503.32
#Mann= 6 ,-1 , 0
       0     .06       0  190.25     .12       0   201.3    .045       0
   216.3     .12       0  698.25     .06       0  761.27     .12       0
#XS Ineff= 2 , 0
          190.71  501.28  225.39          500.89
Permanent Ineff=
       F       F
Bank Sta=201.3,216.3
XS Rating Curve= 0 ,0
Exp/Cntr=0.3,0.1

Type RM Length L Ch R = 1 ,614.3   ,243.5,244.2,244.7
XS GIS Cut Line= 2
     2349232.079      329346.537     2348750.626      328939.064
#Sta/Elev= 30
       0  498.46  160.79499.0627   195.6  500.01   225.2  499.16   227.5  499.27
   231.5  498.81  233.79  498.02   239.5  497.17   243.5  497.36  246.82     498
   251.5  500.31   255.5  500.48   263.5  499.32   287.4  498.95   315.4  499.35
   327.4  498.61   339.3  498.38   403.2  498.52   411.2  498.71   415.2  499.14
   423.2  500.83   427.2  501.35   431.1   501.4   447.1  498.38   455.1  496.03
   463.1  496.85     479  497.74     491  499.44     527  500.88   630.7  500.36
#Mann= 5 ,-1 , 0
       0     .06       0  160.79     .12       0   225.2    .045       0
  233.79    .045       0  246.82     .12       0
#XS Ineff= 2 , 0
          195.05  500.14  256.45          500.59
Permanent Ineff=
       F       F
Bank Sta=233.79,246.82
XS Rating Curve= 0 ,0
Exp/Cntr=0.3,0.1

Type RM Length L Ch R = 1 ,370.1   ,263.8,264.9,265.6
XS GIS Cut Line= 2
     2349363.597      329195.056     2348936.162      328762.923
#Sta/Elev= 30
       0  497.37   88.91497.3969     108  497.39     132  498.18   137.6  496.13
     140  495.19     148  494.63     156  495.38     164   498.8     168  499.61
   187.9  498.86   235.9     499   251.9  499.45   267.9  499.03   275.9   499.3
   287.9  498.79   315.9   499.5   327.9  500.36   351.9  499.13   379.9  500.41
   391.9  498.76   395.9  496.98   399.9  495.96   403.9  495.97   411.9  499.88
   415.9  500.84   419.9  501.13  441.29 500.563   483.8  499.82   607.8  500.04
#Mann= 6 ,-1 , 0
       0     .06       0   88.91     .12       0   137.6    .045       0
     140    .045       0     156     .12       0  441.29     .06       0
#XS Ineff= 2 , 0
          131.48  498.69  169.76          499.81
Permanent Ineff=
       F       F
Bank Sta=140,156
XS Rating Curve= 0 ,0
Exp/Cntr=0.3,0.1

Type RM Length L Ch R = 1 ,105.2   ,102.8,105.2,107.5
XS GIS Cut Line= 2
      2349496.29      329064.711     2349122.871       328646.67
#Sta/Elev= 30
       0  498.37    79.5  499.01   139.1  497.98     167  499.45   186.8  498.77
   214.7  500.17   222.6   499.7   226.6  497.93   230.6  495.31   235.1  493.53
  236.26  493.31   242.5  491.98   246.5  491.87  250.98   493.3   254.4   494.3
   274.3  495.81   290.2   495.4   298.2  495.81   306.1  497.18   314.1  500.09
   341.9  500.81   353.8  500.32   357.8  499.17   369.7  493.86   373.7  493.15
   377.7  494.81   381.6   498.2   385.6   499.5  412.74499.3049   560.5  498.79
#Mann= 5 ,-1 , 0
       0     .12       0   235.1    .045       0  236.26    .045       0
  250.98     .12       0  412.74     .06       0
#XS Ineff= 2 , 0
          213.62  500.34  276.78          501.23
Permanent Ineff=
       F       F
Bank Sta=236.26,250.98
XS Rating Curve= 0 ,0
Exp/Cntr=0.3,0.1

Chan Stop Cuts=-1
Use User Specified Reach Order=0
Composite Channel Slope=5